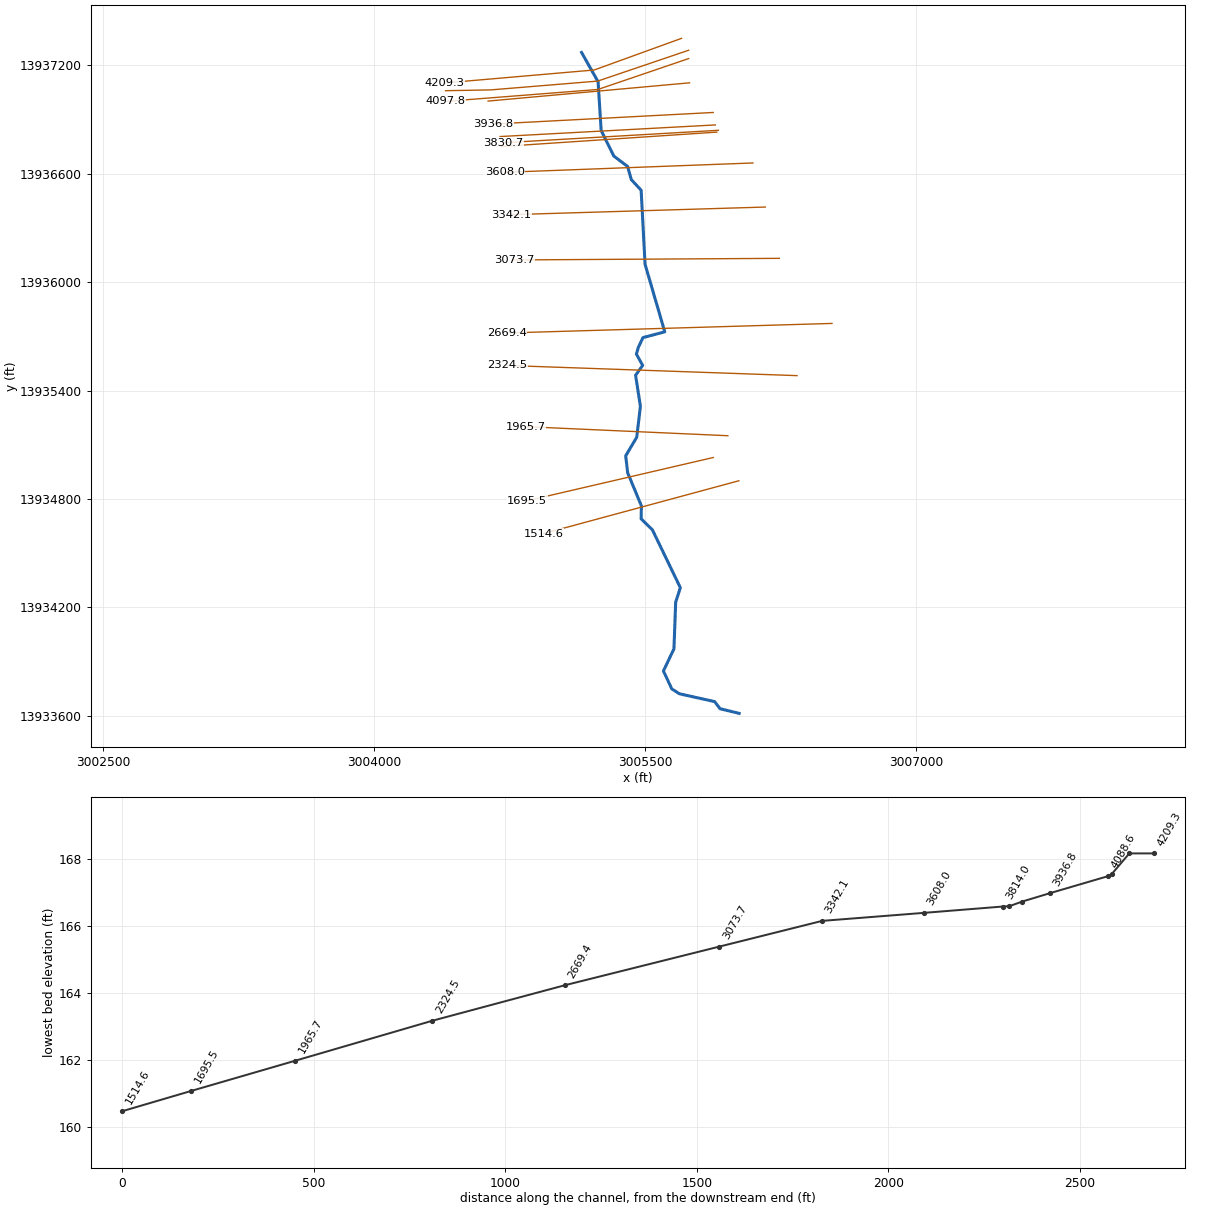
--- L109-00-00.prj (project) ---

Proj Title=L1090000
Current Plan=p02
Default Exp/Contr=.3,.1
English Units
Geom File=g01
Flow File=f01
Flow File=f02
Plan File=p01
Plan File=p02
Y Axis Title=Elevation
X Axis Title(PF)=Main Channel Distance
X Axis Title(XS)=Station
BEGIN DESCRIPTION:
HCFCD Watershed Unit ID: L
M3 Study Identifier: 2007_Effective_L
Engineer: HCFCD
Project Name: EffectiveFEMA Study for watershed Little Cypress Creek (L)
Study Completion Date: 6/18/2007
FEMA Case Number: [No Data]
FEMA Approval Date: [No Date in Database]
Vertical Datum: NAVD 1988
Datum Note: 2001 ADJ
HYDRAULICS
HCFCD Unit No.:  L109-00-00
Hydraulic Program Name: HEC-RAS
Hydraulic Program Version: 3.0.1
Steady Hydraulic Model: Yes
Unsteady Hydraulic Model: No
Update1:
The effective FEMA hydraulic model for unit number L109-00-00 has been updated by FEMA LOMR 13-06-4126P with an effective date of 4/09/2015.
END DESCRIPTION:
DSS Export Rating Curves= 0
DSS Export Rating Curve Sorted= 0
DSS Export Volume Flow Curves= 0
DXF OffsetX= 0
DXF OffsetY= 0
DXF ScaleX= 1
DXF ScaleY= 10

--- L109-00-00.p02 (plan) ---

Plan Title=Effective Floodway 2014
Program Version=4.10
Short Identifier=Eff+LOMR FW
Geom File=g01
Flow File=f02
Subcritical Flow
K Sum by GR= 0
Std Step Tol= 0.01
Critical Tol= 0.01
Num of Std Step Trials= 20
Max Error Tol= 0.3
Flow Tol Ratio= 0.001
Split Flow NTrial= 30
Split Flow Tol= 0.02
Split Flow Ratio= 0.02
Log Output Level= 0
Friction Slope Method= 1
Unsteady Friction Slope Method= 2
Unsteady Bridges Friction Slope Method= 1
Parabolic Critical Depth
Global Vel Dist= 0 , 0 , 0
Global Log Level= 0
CheckData=True
Encroach Param=-1 ,0,0, 2
Encroach River=L109-00-00
Encroach Reach=L109-00-00_0007
Encroach Node=4209.3
       1  4942.4    5190
Encroach Node=4143.8
       1  4942.4    5170
Encroach Node=4120.8
       1  4942.4    5170
Encroach Node=4097.8
       1  4942.4    5170
Encroach Node=4088.6
       1  4942.4 5142.09
Encroach Node=3936.8
       1    4920    5180
Encroach Node=3864.7
       1    4900    5180
Encroach Node=3847.7
       1    4900    5180
Encroach Node=3830.7
       1    4900    5180
Encroach Node=3814.0
       1    4900    5185
Encroach Node=3608.0
       1  4954.4    5235
Encroach Node=3342.1
       1  4954.4    5189
Encroach Node=3073.7
       1    4925    5210
Encroach Node=2669.4
       1    4960    5160
Encroach Node=2324.5
       1    4925    5090
Encroach Node=1965.7
       1    4975 5090.35
Encroach Node=1695.5
       1    4930    5055
Encroach Node=1514.6
       1    4905    5070
Encroach Node=1452.3
       1    4895    5060
Encroach Node=1431.3
       1    4895    5060
Encroach Node=1410.3
       1    4895    5060
Encroach Node=1371.4
       1    4920 5090.73
Encroach Node=1042.4
       1    4880    5075
Encroach Node=669.2
       1 4821.07    5230
BEGIN DESCRIPTION:
FEMA Effective June 2007 + LOMR 13-06-4126P
END DESCRIPTION:
Computation Interval=1HOUR
Output Interval=1HOUR
Run HTab= 0
Run UNet= 0
Run PostProcess= 0
Run WQNet= 0
UNET Theta= 1
UNET Theta Warmup= 1
UNET ZTol= 0.02
UNET ZSATol= 0.1
UNET MxIter= 20
UNET MaxInSteps= 20
UNET DtIC= 0
UNET DtMin= 0
UNET MaxCRTS= 20
UNET WFStab= 2
UNET SFStab= 1
UNET WFX= 1
UNET SFX= 1
UNET DSS MLevel= 4
UNET DZMax Abort= 100
UNET Convert EG Bridges=-1
UNET Use Existing IB Tables=-1
UNET Froude Reduction=False
UNET Froude Limit= 1
UNET Froude Power= 10
UNET Time Slicing=0,0, 5
UNET Junction Losses=0
Instantaneous Interval=1HOUR
Write IC File= 0
Write IC File at Sim End=0
Echo Input=False
Echo Parameters=False
Echo Output=False
Write Detailed= 0
WQ AD Non Conservative
WQ ULTIMATE=-1
WQ Max Comp Step=1HOUR
WQ Output Interval=15MIN
WQ Output Selected Increments= 0
WQ Output face flow=0
WQ Output face velocity=0
WQ Output face area=0
WQ Output face dispersion=0
WQ Output cell volume=0
WQ Output cell surface area=0
WQ Output cell continuity=0
WQ Output cumulative cell continuity=0
WQ Output face conc=0
WQ Output face dconc_dx=0
WQ Output face courant=0
WQ Output face peclet=0
WQ Output face adv mass=0
WQ Output face disp mass=0
WQ Output cell mass=0
WQ Output cell source sink temp=0
WQ Output cell source sink nsm=0
WQ Output MaxMinRange=-1
WQ Daily Max Min Mean=-1
WQ Daily Range=0
WQ Daily Time=0
WQ Create Restart=0
WQ Fixed Restart=0
WQ System Summary=0
WQ Use Fixed Temperature=0
Sorting and Armoring Iterations= 10
XS Update Threshold= 0.02
Hydraulics Update Threshold= 0.02
Energy Slope Method= 1
Volume Change Method= 0
XS Weighting Method= 0
Number of US Weighted Cross Sections= 1
Number of DS Weighted Cross Sections= 1
Upstream XS Weight=0.25
Main XS Weight=0.5
Downstream XS Weight=0.25
Number of DS XS's Weighted with US Boundary= 1
Upstream Boundary Weight= 1
Weight of XSs Associated with US Boundary= 0
Number of US XS's Weighted with DS Boundary= 1
Downstream Boundary Weight= 0.5
Weight of XSs Associated with DS Boundary= 0.5
Sediment Output Level= 4
Mass or Volume Output= 0
Output Increment Type= 1
Profile and TS Output Increment= 10
XS Output Flag= 0
XS Output Increment= 10
Disregard all LS=0
Disregard all Conn=0
Disregard all Breaches=0
Disregard all Pumps=0

--- L109-00-00.p01 (plan) ---

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Plan Title=Effective Multi-Profile 2014
Short Identifier=Eff+LOMR MP
Geom File=g01
Flow File=f01
Encroach Param=-1 ,0,0, 0
IC Time=0,,

--- L109-00-00.f02 (steady flow) ---

Flow Title=Floodway
Program Version=4.10
Number of Profiles= 2
Profile Names=1PCT_100yr,1PCTFloodway_100yr
River Rch & RM=L109-00-00,L109-00-00_0007 ,4209.3
     490     490
River Rch & RM=L109-00-00,L109-00-00_0007 ,4088.6
     526     526
River Rch & RM=L109-00-00,L109-00-00_0007 ,3814.0
     554     554
River Rch & RM=L109-00-00,L109-00-00_0007 ,3608.0
     593     593
River Rch & RM=L109-00-00,L109-00-00_0007 ,3342.1
     636     636
River Rch & RM=L109-00-00,L109-00-00_0007 ,3073.7
     705     705
River Rch & RM=L109-00-00,L109-00-00_0007 ,2669.4
     732     732
River Rch & RM=L109-00-00,L109-00-00_0007 ,1965.7
     785     785
Boundary for River Rch & Prof#=L109-00-00,L109-00-00_0007 , 1
Up Type= 0
Dn Type= 3
Dn Slope=0.004
Boundary for River Rch & Prof#=L109-00-00,L109-00-00_0007 , 2
Up Type= 0
Dn Type= 1
Dn Known WS=166.61
DSS Import GetInterval= 0
DSS Import GetPeak= 0
DSS Import FillOption= 0

--- L109-00-00.f01 (steady flow) ---

Flow Title=FEMA Effective Multi-Profile
Program Version=4.10
Number of Profiles= 4
Profile Names=10PCT_10yr,2PCT_50yr,1PCT_100yr,0.2PCT_500yr
River Rch & RM=L109-00-00,L109-00-00_0007 ,4209.3
     260     415     490     719
River Rch & RM=L109-00-00,L109-00-00_0007 ,4088.6
     279     445     526     772
River Rch & RM=L109-00-00,L109-00-00_0007 ,3814.0
     294     469     554     814
River Rch & RM=L109-00-00,L109-00-00_0007 ,3608.0
     314     503     593     871
River Rch & RM=L109-00-00,L109-00-00_0007 ,3342.1
     337     538     636     933
River Rch & RM=L109-00-00,L109-00-00_0007 ,3073.7
     374     597     705    1035
River Rch & RM=L109-00-00,L109-00-00_0007 ,2669.4
     388     620     732    1075
River Rch & RM=L109-00-00,L109-00-00_0007 ,1965.7
     416     665     785    1152
Boundary for River Rch & Prof#=L109-00-00,L109-00-00_0007 , 1
Up Type= 0
Dn Type= 3
Dn Slope=0.004
Boundary for River Rch & Prof#=L109-00-00,L109-00-00_0007 , 2
Up Type= 0
Dn Type= 3
Dn Slope=0.004
Boundary for River Rch & Prof#=L109-00-00,L109-00-00_0007 , 3
Up Type= 0
Dn Type= 3
Dn Slope=0.004
Boundary for River Rch & Prof#=L109-00-00,L109-00-00_0007 , 4
Up Type= 0
Dn Type= 3
Dn Slope=0.004
DSS Import GetInterval= 0
DSS Import GetPeak= 0
DSS Import FillOption= 0

--- L109-00-00.g01 (geometry) ---

Geom Title=L109-00-00
Version=Version 3.0.1  May 2012

River Reach=L109-00-00      ,L109-00-00_0007
Reach XY= 30
      3005148.75       13937272.    3005240.2099   13937109.8221
    3005257.0396   13936840.2178        3005327.       13936699.
     3005403.741    13936640.565    3005423.7063   13936568.5164
    3005478.3938   13936509.4886    3005500.1223    13936099.685
    3005609.1692   13935725.6866    3005488.5095   13935693.5685
    3005463.3359   13935640.6171    3005452.0512   13935602.4227
    3005486.7734   13935539.9227    3005447.7109   13935485.2352
    3005474.3519   13935313.0097    3005454.0068   13935142.1112
    3005392.9717   13935039.0296    3005403.8224   13934945.4424
    3005479.7772   13934762.3369    3005478.4209   13934690.4511
    3005540.8124   13934629.4159    3005695.4348   13934309.3204
    3005669.6644   13934229.2965    3005659.9798   13933970.6731
    3005601.8475   13933848.1659     3005647.963   13933749.1533
    3005690.0094   13933722.0266    3005885.3219   13933678.6238
    3005915.1613     13933639.29    3006020.9547   13933613.5199

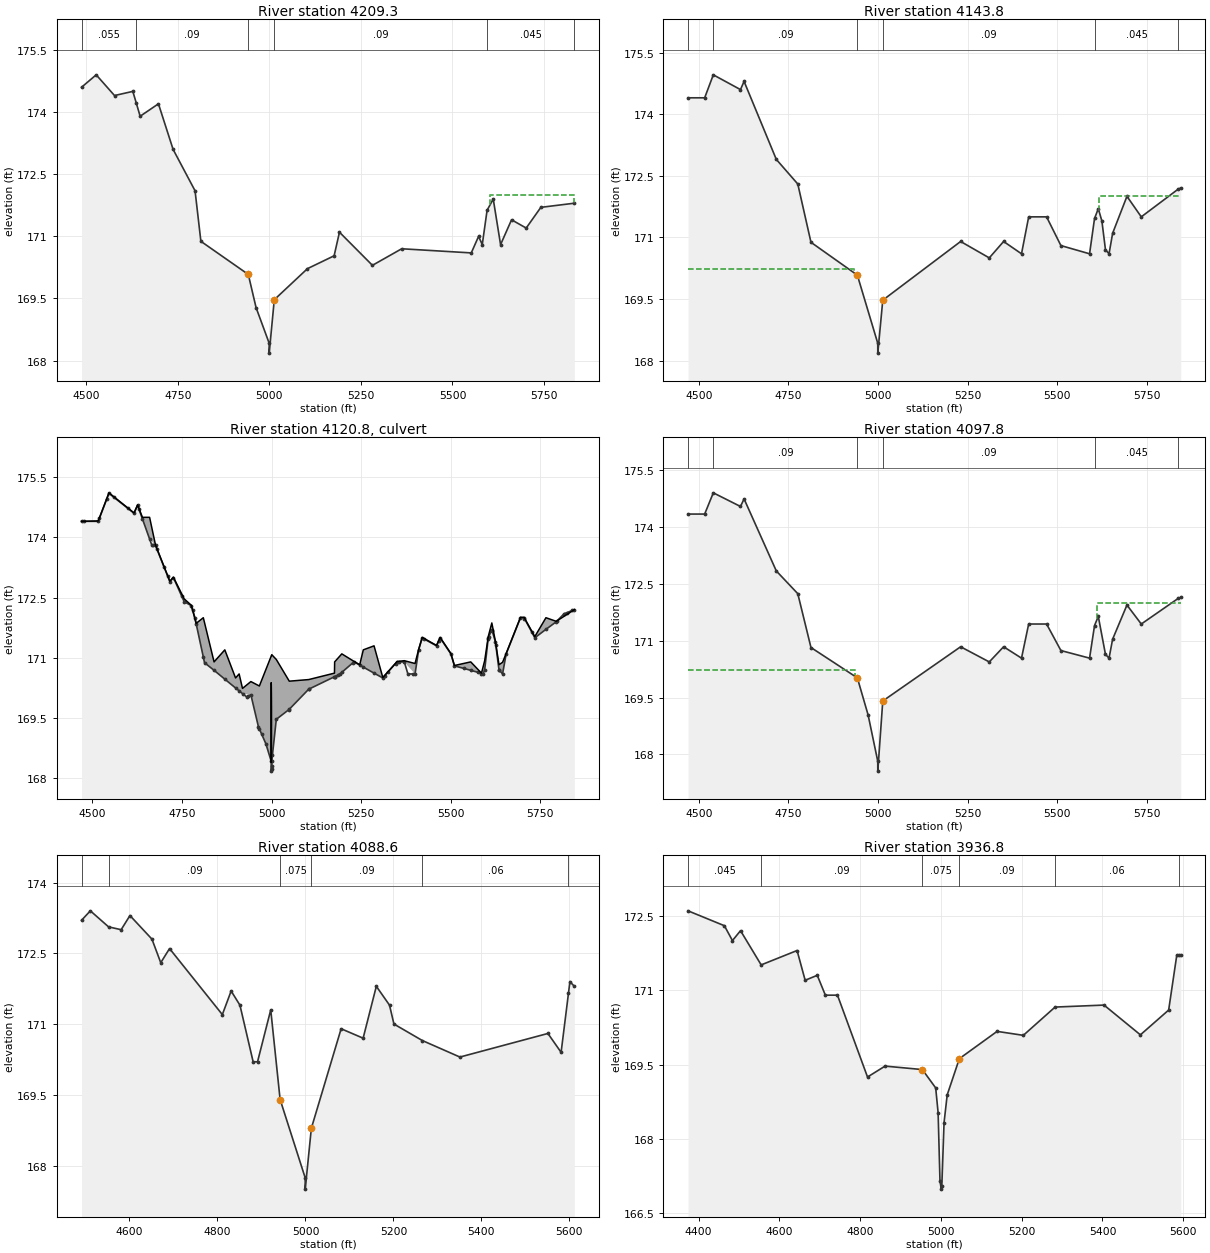
Type RM Length L Ch R = 1 ,4209.3  ,66.9,65.5,61.6
BEGIN DESCRIPTION:
Cross Section XS15
END DESCRIPTION:
XS GIS Cut Line= 3
    3005702.1981   13937350.2866    3005218.5928   13937175.0351
    3004390.2461    13937103.153
#Sta/Elev= 30
    4487   174.6    4527   174.9    4577   174.4    4627   174.5  4636.1  174.23
    4647   173.9    4697   174.2    4737   173.1    4797   172.1  4812.9  170.88
  4942.4  170.08  4963.6  169.28  4999.4  168.42  4999.5  168.18  5013.4  169.47
    5104  170.22  5176.8  170.53  5191.4   171.1  5281.4   170.3  5361.4   170.7
  5551.4   170.6  5571.4     171  5581.4   170.8  5594.6  171.63  5611.4   171.9
  5631.4   170.8  5661.4   171.4  5701.4   171.2  5741.4   171.7  5832.8   171.8
#Mann= 6 ,-1 , 0
    4487    .055       0  4636.1     .09       0  4942.4    .075       0
  5013.4     .09       0  5594.6    .045       0  5832.8      .2       0
#XS Ineff= 2 , 0
       0                    5603       0     172
Permanent Ineff=
       F       F
Bank Sta=4942.4,5013.4
XS Rating Curve= 0
Exp/Cntr=.5,.3

Type RM Length L Ch R = 1 ,4143.8  ,46,46,46
BEGIN DESCRIPTION:
Upstream Section of Bridge/Culvert/Weir
END DESCRIPTION:
XS GIS Cut Line= 4
    3005741.3257   13937284.3576    3005238.1601   13937113.6407
    3004645.8546   13937064.8365      3004395.67   13937060.4506
#Sta/Elev= 30
  4469.6   174.4  4516.1   174.4  4540.2  174.96  4616.1   174.6  4626.1   174.8
  4716.1   172.9  4776.1   172.3  4812.9  170.88  4942.4  170.08  4999.4  168.42
  4999.5  168.18  5013.4  169.47  5230.8   170.9  5310.8   170.5  5350.8   170.9
  5400.8   170.6  5420.8   171.5  5470.8   171.5  5510.8   170.8  5590.8   170.6
  5604.7  171.46  5615.2   171.7  5625.2   171.4  5635.2   170.7  5645.2   170.6
  5655.2   171.1  5695.2     172  5735.2   171.5    5839  172.18  5845.5   172.2
#Mann= 6 ,-1 , 0
  4469.6    .045       0  4540.2     .09       0  4942.4    .075       0
  5013.4     .09       0  5604.7    .045       0    5839      .2       0
#XS Ineff= 2 , 0
       0  4932.4  170.24    5617       0     172
Permanent Ineff=
       F       F
Bank Sta=4942.4,5013.4
XS Rating Curve= 0
Exp/Cntr=.5,.3

Type RM Length L Ch R = 2 ,4120.8  ,,,
BEGIN DESCRIPTION:
WILKS DRIVE
Structure ID: L109-00-00-S02B
END DESCRIPTION:
Bridge Culvert--1,0,-1,-1, 0
Deck Dist Width WeirC Skew NumUp NumDn MinLoCord MaxHiCord MaxSubmerge Is_Ogee
10,26,3,0, 60, 55, , , .95, 0, 1,1,,
  4469.6  4516.1  4546.1  4616.1  4626.1  4639.6  4659.6  4676.1  4716.1  4726.1
  4756.1  4776.1  4789.6  4809.6  4812.9  4839.6  4869.6  4899.6  4909.6    4919
  4942.4  4966.1  4999.4  4999.5  5000.7  5013.4  5049.6  5103.9  5175.8  5176.3
  5196.3  5230.8  5246.3  5256.3  5286.3  5310.8  5350.8  5370.8  5400.8  5410.8
  5420.8  5460.8  5470.8  5500.8  5510.8  5556.3  5586.3  5595.2  5605.2  5615.2
  5625.2  5635.2  5645.2  5655.2  5695.2  5705.2  5735.2  5766.3  5795.2  5845.5
   174.4  174.41  175.11  174.61  174.81   174.5   174.5  173.81  172.91  173.01
  172.47  172.31  171.86     172  171.88   170.9   171.2   170.5   170.6  170.24
  170.41   170.3  171.05  171.05  171.08  170.96  170.42  170.46  170.62   170.9
   171.1  170.91  170.83   171.2   171.3  170.51  170.91  170.93  170.86  171.21
  171.51  171.31  171.51  171.11  170.81   170.9  170.62  170.93  171.53  171.87
  171.41  170.83  170.89  171.11  172.01  172.01  171.53     172  171.91   172.2
   174.4   174.4   175.1   174.6   174.8  174.46  173.96   173.8   172.9     173
   172.4   172.3  171.85  171.02  170.88  170.69  170.47  170.25  170.18  170.11
  170.08  169.23  168.42  168.18  168.42  169.47  169.72  170.22  170.53  170.53
  170.64   170.9  170.82  170.77  170.62   170.5   170.9   170.9   170.6   171.2
   171.5   171.3   171.5   171.1   170.8  170.69  170.61   170.7   171.5   171.7
   171.4   170.7   170.6   171.1     172     172   171.5  171.71   171.9   172.2
  4469.6  4516.1  4546.1  4616.1  4626.1  4639.6  4659.6  4676.1  4716.1  4726.1
  4756.1  4776.1  4789.6  4809.6  4839.6  4869.6  4899.6  4909.6    4919  4934.8
  4966.1  5002.7  5049.6  5175.8  5176.3  5186.3  5196.3  5226.3  5246.3  5256.3
  5286.3  5310.8  5356.3  5396.3  5400.8  5420.8  5460.8  5470.8  5500.8  5510.8
  5536.3  5556.3  5586.3  5590.8  5606.3  5616.3  5636.3  5645.2  5695.2  5705.2
  5735.2  5766.3  5795.2  5817.1  5845.5
   174.4  174.41  175.11  174.61  174.81   174.5   174.5  173.81  172.91  173.01
  172.47  172.31  171.86     172   170.9   171.2   170.5   170.6  170.24  170.44
   170.3  171.12  170.42  170.62   170.9   170.9   171.1  170.88  170.83   171.2
   171.3  170.51     171   170.8  170.86  171.51  171.31  171.51  171.11  170.81
  170.75   170.9  170.62  170.67   171.6   171.9   170.8  170.89  172.01  172.01
  171.53     172  171.91  172.11   172.2
                                                                                
                                                                                
                                                                                
                                                                                
                                                                                
                                        
BR Coef= 1 , 0 , 0 ,1.25, 0 ,,,.8,-1,2,0,
WSPro=,,,, 1 ,,,, 0 ,,,, 0 ,,,,-1 ,-1 ,-1 , 0 , 0 , 0 , 0 , 0
Culvert=1,2,,26,.015,.5,1,1,3,168.39,4999.2,168.06,4999.2,Culvert #1  , 0 ,10
Culvert Bottom n=.015
BR U #Sta/Elev= 110
  4469.6   174.4  4476.1   174.4  4516.1   174.4  4519.6  174.48  4540.2  174.96
  4546.1   175.1  4559.6     175  4599.6  174.72  4616.1   174.6  4626.1   174.8
  4629.6  174.71  4639.6  174.46  4659.6  173.96  4666.1   173.8  4669.6   173.8
  4676.1   173.8  4679.6  173.72  4699.6  173.27  4709.6  173.05  4716.1   172.9
  4726.1     173  4749.6  172.53  4756.1   172.4  4776.1   172.3  4779.6   172.2
  4786.1     172  4789.6  171.85  4809.6  171.02  4812.9  170.88  4839.6  170.69
  4869.6  170.47  4899.6  170.25  4909.6  170.18    4919  170.11  4930.5  170.03
  4934.8  170.05  4942.4  170.08  4963.6  169.28  4966.1  169.23  4972.5   169.1
  4984.3  168.86  4999.4  168.42  4999.5  168.18  5000.1  168.24  5000.6  168.32
  5000.7  168.42  5002.7  168.59  5013.4  169.47  5048.3  169.71  5049.6  169.72
  5103.9  170.22    5104  170.22  5175.8  170.53  5176.3  170.53  5176.8  170.53
  5186.3  170.58  5190.8   170.6  5196.3  170.64  5226.3  170.87  5230.8   170.9
  5246.3  170.82  5256.3  170.77  5286.3  170.62  5310.8   170.5  5316.3  170.56
  5326.3  170.66  5346.3  170.86  5350.8   170.9  5356.3   170.9  5370.8   170.9
  5380.8   170.6  5396.3   170.6  5400.8   170.6  5410.8   171.2  5420.8   171.5
  5426.3  171.47  5460.8   171.3  5466.3  171.41  5470.8   171.5  5500.8   171.1
  5510.8   170.8  5536.3  170.74  5556.3  170.69  5576.3  170.64  5586.3  170.61
  5590.8   170.6  5595.2   170.7  5604.7  171.46  5605.2   171.5  5606.3  171.52
  5615.2   171.7  5616.3  171.67  5625.2   171.4  5626.3  171.32  5635.2   170.7
  5636.3  170.69  5645.2   170.6  5655.2   171.1  5695.2     172  5705.2     172
  5706.3  171.98  5726.3  171.65  5735.2   171.5  5766.3  171.71  5795.2   171.9
  5796.3  171.91  5817.1   172.1  5826.3  172.13    5839  172.18  5845.5   172.2
BR U #Mann= 6
  4469.6    .045  4540.2     .09  4942.4    .075  5013.4     .09  5604.7    .045
    5839      .2
BR U Banks=4942.4,5013.4
BR D #Sta/Elev= 110
  4469.6  174.34  4476.1  174.34  4516.1  174.34  4519.6  174.42  4540.2   174.9
  4546.1  175.04  4559.6  174.94  4599.6  174.66  4616.1  174.54  4626.1  174.74
  4629.6  174.65  4639.6   174.4  4659.6   173.9  4666.1  173.74  4669.6  173.74
  4676.1  173.74  4679.6  173.66  4699.6  173.21  4709.6  172.99  4716.1  172.84
  4726.1  172.94  4749.6  172.47  4756.1  172.34  4776.1  172.24  4779.6  172.14
  4786.1  171.94  4789.6  171.79  4809.6  170.96  4812.9  170.82  4839.6  170.63
  4869.6  170.41  4899.6  170.19  4909.6  170.12    4919  170.05  4930.5  169.97
  4934.8  169.99  4942.4  170.02  4963.6  169.22  4966.1  169.17  4972.5  169.04
  4984.3   168.4  4999.4  167.82  4999.5  167.56  5000.1  167.62  5000.6   167.7
  5000.7  167.82  5002.7   168.1  5013.4  169.41  5048.3  169.65  5049.6  169.66
  5103.9  170.16    5104  170.16  5175.8  170.47  5176.3  170.47  5176.8  170.47
  5186.3  170.52  5190.8  170.54  5196.3  170.58  5226.3  170.81  5230.8  170.84
  5246.3  170.76  5256.3  170.71  5286.3  170.56  5310.8  170.44  5316.3   170.5
  5326.3   170.6  5346.3   170.8  5350.8  170.84  5356.3  170.84  5370.8  170.84
  5380.8  170.54  5396.3  170.54  5400.8  170.54  5410.8  171.14  5420.8  171.44
  5426.3  171.41  5460.8  171.24  5466.3  171.35  5470.8  171.44  5500.8  171.04
  5510.8  170.74  5536.3  170.68  5556.3  170.63  5576.3  170.58  5586.3  170.55
  5590.8  170.54  5595.2  170.64  5604.7   171.4  5605.2  171.44  5606.3  171.46
  5615.2  171.64  5616.3  171.61  5625.2  171.34  5626.3  171.26  5635.2  170.64
  5636.3  170.63  5645.2  170.54  5655.2  171.04  5695.2  171.94  5705.2  171.94
  5706.3  171.92  5726.3  171.59  5735.2  171.44  5766.3  171.65  5795.2  171.84
  5796.3  171.85  5817.1  172.04  5826.3  172.07    5839  172.12  5845.5  172.14
BR D #Mann= 6
  4469.6    .045  4540.2     .09  4942.4    .075  5013.4     .09  5604.7    .045
    5839      .2
BR D Banks=4942.4,5013.4
BC Design=,, 0 ,, 0 ,,,,,,
BC HTab HWMax=175.1

Type RM Length L Ch R = 1 ,4097.8  ,9.2,9.2,9.2
BEGIN DESCRIPTION:
Downstream Section of Bridge/Culvert/Weir
END DESCRIPTION:
XS GIS Cut Line= 3
    3005741.4556   13937238.2703    3005239.5064   13937067.3007
    3004396.3695    13937001.335
#Sta/Elev= 30
  4469.6  174.34  4516.1  174.34  4540.2   174.9  4616.1  174.54  4626.1  174.74
  4716.1  172.84  4776.1  172.24  4812.9  170.82  4942.4  170.02  4972.5  169.04
  4999.4  167.82  4999.5  167.56  5013.4  169.41  5230.8  170.84  5310.8  170.44
  5350.8  170.84  5400.8  170.54  5420.8  171.44  5470.8  171.44  5510.8  170.74
  5590.8  170.54  5604.7   171.4  5615.2  171.64  5635.2  170.64  5645.2  170.54
  5655.2  171.04  5695.2  171.94  5735.2  171.44    5839  172.12  5845.5  172.14
#Mann= 6 ,-1 , 0
  4469.6    .045       0  4540.2     .09       0  4942.4    .075       0
  5013.4     .09       0  5604.7    .045       0    5839      .2       0
#XS Ineff= 2 , 0
       0 4935.73  170.24    5612       0     172
Permanent Ineff=
       F       F
Bank Sta=4942.4,5013.4
XS Rating Curve= 0
Exp/Cntr=.5,.3

Type RM Length L Ch R = 1 ,4088.6  ,151.8,151.8,151.8
BEGIN DESCRIPTION:
Cross Section XS14
END DESCRIPTION:
XS GIS Cut Line= 2
    3005746.5656   13937104.0472    3004631.1738    13937002.967
#Sta/Elev= 30
  4491.1   173.2  4511.1   173.4  4552.5  173.06  4581.1     173  4601.1   173.3
  4651.1   172.8  4671.1   172.3  4691.1   172.6  4811.1   171.2  4831.1   171.7
  4851.1   171.4  4881.1   170.2  4891.1   170.2  4921.1   171.3  4942.4   169.4
  4999.4  167.74  4999.5   167.5  5013.4  168.79  5081.1   170.9  5131.1   170.7
  5161.1   171.8  5191.1   171.4  5201.1     171  5265.7  170.65  5351.1   170.3
  5551.1   170.8  5581.1   170.4  5597.8  171.65  5601.1   171.9  5611.1   171.8
#Mann= 6 ,-1 , 0
  4491.1     .04       0  4552.5     .09       0  4942.4    .075       0
  5013.4     .09       0  5265.7     .06       0  5597.8    .045       0
Bank Sta=4942.4,5013.4
XS Rating Curve= 0
Exp/Cntr=.3,.1

Type RM Length L Ch R = 1 ,3936.8  ,72.1,72.1,72.1
BEGIN DESCRIPTION:
Cross Section XS13
END DESCRIPTION:
XS GIS Cut Line= 2
    3005877.4496   13936939.8876    3004659.1347   13936875.9257
#Sta/Elev= 30
  4373.9   172.6  4463.9   172.3  4483.9     172  4503.9   172.2    4555  171.51
  4643.9   171.8  4663.9   171.2  4693.9   171.3  4713.9   170.9  4743.9   170.9
  4818.3  169.25  4861.8  169.47  4954.1   169.4  4987.1  169.03  4993.1  168.53
  4997.7  167.16  5000.8  166.99  5002.3  167.06  5007.8  168.33  5015.6  168.89
  5045.7  169.62  5139.1  170.17  5204.1  170.09  5282.7  170.66  5403.9   170.7
  5493.9   170.1  5563.9   170.6  5583.9   171.7  5590.5   171.7  5593.9   171.7
#Mann= 6 ,-1 , 0
  4373.9    .045       0    4555     .09       0  4954.1    .075       0
  5045.7     .09       0  5282.7     .06       0  5590.5    .045       0
Bank Sta=4954.1,5045.7
XS Rating Curve= 0
Exp/Cntr=.5,.3

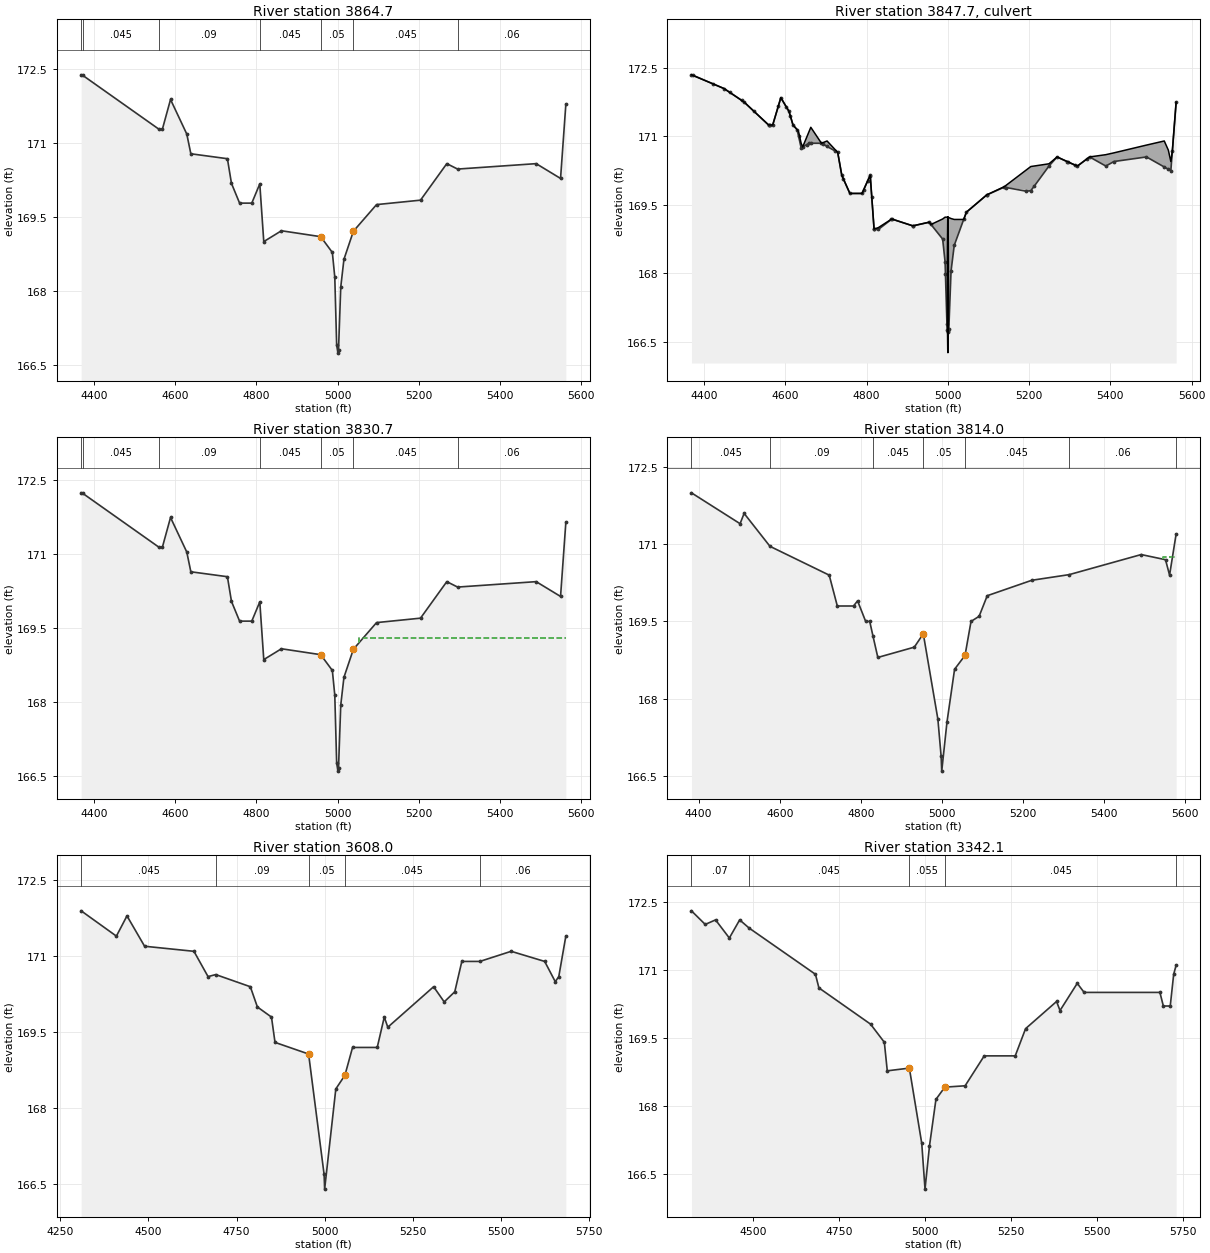
Type RM Length L Ch R = 1 ,3864.7  ,34,34,34
BEGIN DESCRIPTION:
Upstream Section of Bridge/Culvert/Weir
END DESCRIPTION:
XS GIS Cut Line= 2
    3005889.0778   13936870.9631    3004697.8115   13936806.6303
#Sta/Elev= 30
  4368.8  172.38  4372.6  172.37  4559.9  171.28  4568.8  171.28  4588.8  171.88
  4628.8  171.18  4638.8  170.78  4728.8  170.68  4738.8  170.18  4758.8  169.78
  4788.8  169.78  4808.5  170.17  4818.3     169  4861.8  169.22  4958.4   169.1
  4987.1  168.78  4993.1  168.28  4997.7  166.91  5000.8  166.74  5002.3  166.81
  5007.8  168.08  5015.6  168.64  5038.9  169.21  5095.9  169.75  5204.1  169.84
  5268.8  170.58  5295.4  170.47  5488.8  170.58  5548.8  170.28  5561.8  171.78
#Mann= 7 ,-1 , 0
  4368.8      .2       0  4372.6    .045       0  4559.9     .09       0
  4808.5    .045       0  4958.4     .05       0  5038.9    .045       0
  5295.4     .06       0
#XS Ineff= 2 , 0
       0  4944.1  168.97  5055.7       0   169.3
Permanent Ineff=
       F       F
Bank Sta=4958.4,5038.9
XS Rating Curve= 0
Exp/Cntr=.5,.3

Type RM Length L Ch R = 2 ,3847.7  ,,,
BEGIN DESCRIPTION:
1800' DS OF MUESHKE
Structure ID: L109-00-00-S02A
END DESCRIPTION:
Bridge Culvert--1,0,-1,-1, 0
Deck Dist Width WeirC Skew NumUp NumDn MinLoCord MaxHiCord MaxSubmerge Is_Ogee
10,14,3,0, 51, 51, , , .95, 0, 1,1,,
  4368.8  4448.8  4498.8  4558.8  4568.8  4588.8  4608.8  4618.8  4628.8  4632.6
  4638.8  4642.6  4662.6  4688.8  4702.6  4728.8  4738.8  4758.8  4788.8  4808.8
  4818.3  4828.7  4861.8  4913.6  4954.1  4958.4  4987.1  4993.1  4997.7  4998.6
  5000.8  5002.3  5007.8  5015.6  5038.9  5045.7  5095.9  5139.1  5204.1  5248.8
  5268.8  5318.8  5348.8  5388.8  5408.8  5488.8  5532.6  5542.6  5548.8  5552.6
  5561.8
  172.35  172.05  171.75  171.25  171.25  171.85  171.55  171.25  171.15   171.1
  170.85  170.77   171.2  170.85   170.9  170.65  170.15  169.75  169.75  170.15
  168.97     169  169.19  169.04  169.12  169.07  169.19  169.23  169.23  169.23
  169.22  169.22   169.2  169.18  169.18  169.34  169.72   169.9  170.34   170.4
  170.55  170.35  170.55   170.6  170.64  170.81   170.9   170.7  170.45  170.69
  171.75
  172.35  172.05  171.75  171.25  171.25  171.85  171.55  171.25  171.15     171
  170.75  170.77  170.85  170.85  170.78  170.65  170.15  169.75  169.75  170.15
  168.97  168.96  169.19  169.04  169.12  169.07  168.75  168.25  166.88  166.75
  166.71  166.78  168.05  168.61  169.18  169.34  169.72  169.89  169.81  170.35
  170.55  170.35  170.55  170.35  170.45  170.55  170.33  170.28  170.25  170.69
  171.75
  4368.8  4448.8  4498.8  4558.8  4568.8  4588.8  4608.8  4618.8  4628.8  4632.6
  4638.8  4642.6  4662.6  4688.8  4702.6  4728.8  4738.8  4758.8  4788.8  4808.8
  4818.2  4828.7  4861.8  4913.6  4954.1  4958.4  4987.1  4993.1  4997.7  4998.6
  5000.8  5002.3  5007.8  5015.6  5038.9  5045.7  5095.9  5139.1  5204.1  5248.8
  5268.8  5318.8  5348.8  5388.8  5408.8  5488.8  5532.6  5542.6  5548.8  5552.6
  5561.8
   172.3  172.01  171.71  171.21  171.22  171.81  171.51  171.21   171.1   171.1
  170.85  170.73   171.2  170.81   170.9  170.61  170.11  169.71  169.71  170.11
  168.97     169  169.15     169  169.08  169.03  169.19  169.23  169.23  169.23
  169.22  169.22   169.2  169.18  169.14   169.3  169.68   169.9  170.34   170.4
  170.51  170.31  170.51   170.6  170.64  170.81   170.9   170.7  170.45  170.65
   171.7
  172.25  171.95  171.65  171.15  171.15  171.75  171.45  171.15  171.05   170.9
  170.65  170.67  170.75  170.75  170.68  170.55  170.05  169.65  169.65  170.05
  168.88  168.86  169.09  168.94  169.02  168.97  168.65  168.15  166.78  166.65
  166.61  166.68  167.95  168.51  169.08  169.24  169.62  169.79  169.71  170.25
  170.45  170.25  170.45  170.25  170.35  170.45  170.23  170.18  170.15  170.59
  171.65
BR Coef= 1 , 0 , 0 ,1.25, 0 ,,,.8,-1,2,0,
WSPro=,,,, 1 ,,,, 0 ,,,, 0 ,,,,-1 ,-1 ,-1 , 0 , 0 , 0 , 0 , 0
Culvert=1,3,,14,.027,.9,1,2,3,166.25,5000,166.16,5000,Culvert #1  , 0 ,10
Culvert Bottom n=.027
BR U #Sta/Elev= 83
  4368.8  172.35  4372.6  172.34  4422.6  172.15  4448.8  172.05  4462.6  171.97
  4492.6  171.79  4498.8  171.75  4522.6  171.55  4558.8  171.25  4559.9  171.25
  4562.6  171.25  4568.8  171.25  4582.6  171.66  4588.8  171.85  4602.6  171.64
  4608.8  171.55  4612.6  171.44  4618.8  171.25  4628.8  171.15  4632.6     171
  4638.8  170.75  4642.6  170.77  4652.6  170.82  4658.8  170.85  4662.6  170.85
  4688.8  170.85  4692.6  170.83  4702.6  170.78  4722.6  170.68  4728.8  170.65
  4738.8  170.15  4742.6  170.07  4758.8  169.75  4788.8  169.75  4792.6  169.83
  4802.6  170.03  4808.5  170.14  4808.8  170.15  4812.6  169.68  4818.2  168.98
  4818.3  168.97  4828.7  168.96  4860.8  169.18  4861.8  169.19  4913.6  169.04
  4914.7  169.04  4954.1  169.12  4958.4  169.07  4987.1  168.75  4993.1  168.25
    4994  167.98  4997.7  166.88  4998.6  166.75  4999.3  166.73  5000.8  166.71
  5002.3  166.78  5007.8  168.05  5015.6  168.61  5038.9  169.18  5045.7  169.34
  5095.9  169.72  5096.5  169.72  5139.1  169.89  5143.3  169.88  5192.3   169.8
  5204.1  169.81  5212.6  169.91  5248.8  170.35  5268.8  170.55  5292.6  170.45
  5295.4  170.44  5312.6  170.37  5318.8  170.35  5342.6  170.51  5348.8  170.55
  5388.8  170.35  5408.8  170.45  5488.8  170.55  5532.6  170.33  5542.6  170.28
  5548.8  170.25  5552.6  170.69  5561.8  171.75
BR U #Mann= 7
  4368.8      .2  4372.6    .045  4559.9     .09  4808.5    .045  4958.4     .05
  5038.9    .045  5295.4     .06
BR U Banks=4958.4,5038.9
BR D #Sta/Elev= 83
  4368.8  172.25  4372.6  172.24  4422.6  172.05  4448.8  171.95  4462.6  171.87
  4492.6  171.69  4498.8  171.65  4522.6  171.45  4558.8  171.15  4559.9  171.15
  4562.6  171.15  4568.8  171.15  4582.6  171.56  4588.8  171.75  4602.6  171.54
  4608.8  171.45  4612.6  171.34  4618.8  171.15  4628.8  171.05  4632.6   170.9
  4638.8  170.65  4642.6  170.67  4652.6  170.72  4658.8  170.75  4662.6  170.75
  4688.8  170.75  4692.6  170.73  4702.6  170.68  4722.6  170.58  4728.8  170.55
  4738.8  170.05  4742.6  169.97  4758.8  169.65  4788.8  169.65  4792.6  169.73
  4802.6  169.93  4808.5  170.04  4808.8  170.05  4812.6  169.58  4818.2  168.88
  4818.3  168.87  4828.7  168.86  4860.8  169.08  4861.8  169.09  4913.6  168.94
  4914.7  168.94  4954.1  169.02  4958.4  168.97  4987.1  168.65  4993.1  168.15
    4994  167.88  4997.7  166.78  4998.6  166.65  4999.3  166.63  5000.8  166.61
  5002.3  166.68  5007.8  167.95  5015.6  168.51  5038.9  169.08  5045.7  169.24
  5095.9  169.62  5096.5  169.62  5139.1  169.79  5143.3  169.78  5192.3   169.7
  5204.1  169.71  5212.6  169.81  5248.8  170.25  5268.8  170.45  5292.6  170.35
  5295.4  170.34  5312.6  170.27  5318.8  170.25  5342.6  170.41  5348.8  170.45
  5388.8  170.25  5408.8  170.35  5488.8  170.45  5532.6  170.23  5542.6  170.18
  5548.8  170.15  5552.6  170.59  5561.8  171.65
BR D #Mann= 7
  4368.8      .2  4372.6    .045  4559.9     .09  4808.5    .045  4958.4     .05
  5038.9    .045  5295.4     .06
BR D Banks=4958.4,5038.9
BC Design=,, 0 ,, 0 ,,,,,,
BC HTab HWMax=172.38

Type RM Length L Ch R = 1 ,3830.7  ,16.7,16.7,16.7
BEGIN DESCRIPTION:
Downstream Section of Bridge/Culvert/Weir
END DESCRIPTION:
XS GIS Cut Line= 2
    3005905.5507   13936841.1765    3004714.5062   13936772.2915
#Sta/Elev= 30
  4368.8  172.24  4372.6  172.23  4559.9  171.14  4568.8  171.14  4588.8  171.74
  4628.8  171.04  4638.8  170.64  4728.8  170.54  4738.8  170.04  4758.8  169.64
  4788.8  169.64  4808.5  170.03  4818.3  168.86  4861.8  169.08  4958.4  168.96
  4987.1  168.64  4993.1  168.14  4997.7  166.77  5000.8   166.6  5002.3  166.67
  5007.8  167.94  5015.6   168.5  5038.9  169.07  5095.9  169.61  5204.1   169.7
  5268.8  170.44  5295.4  170.33  5488.8  170.44  5548.8  170.14  5561.8  171.64
#Mann= 7 ,-1 , 0
  4368.8      .2       0  4372.6    .045       0  4559.9     .09       0
  4808.5    .045       0  4958.4     .05       0  5038.9    .045       0
  5295.4     .06       0
#XS Ineff= 2 , 0
       0 4947.43  168.97 5052.37       0   169.3
Permanent Ineff=
       F       F
Bank Sta=4958.4,5038.9
XS Rating Curve= 0
Exp/Cntr=.5,.3

Type RM Length L Ch R = 1 ,3814.0  ,182.78,206,241.54
BEGIN DESCRIPTION:
Cross Section XS12
END DESCRIPTION:
XS GIS Cut Line= 2
    3005897.4149   13936831.1873    3004703.9303   13936751.3259
#Sta/Elev= 29
  4382.2     172  4502.2   171.4  4512.2   171.6    4576  170.96  4722.2   170.4
  4742.2   169.8  4782.2   169.8  4792.2   169.9  4812.2   169.5  4822.2   169.5
  4830.1  169.22  4842.2   168.8  4932.2     169  4954.4  169.26  4990.4   167.6
  4998.4  166.88  4999.9  166.59  5012.8  167.54  5031.6  168.57  5057.4  168.84
  5072.2   169.5  5092.2   169.6  5112.2     170  5222.2   170.3  5314.6  170.41
  5492.2   170.8  5552.2   170.7  5562.2   170.4  5578.4   171.2
#Mann= 7 ,-1 , 0
  4382.2    .045       0    4576     .09       0  4830.1    .045       0
  4954.4     .05       0  5057.4    .045       0  5314.6     .06       0
  5578.4      .2       0
#XS Ineff= 2 , 0
       0                    5545       0  170.75
Permanent Ineff=
       F       F
Bank Sta=4954.4,5057.4
XS Rating Curve= 0
Exp/Cntr=.3,.1

Type RM Length L Ch R = 1 ,3608.0  ,253.88,265.9,247.57
BEGIN DESCRIPTION:
Cross Section XS11
END DESCRIPTION:
XS GIS Cut Line= 3
    3006097.0685   13936660.3726    3004801.5387   13936611.5684
 3004722.894287913936608.6057683
#Sta/Elev= 30
  4309.1   171.9  4409.1   171.4  4439.1   171.8  4489.1   171.2  4629.1   171.1
  4669.1   170.6  4690.9  170.64  4789.1   170.4  4809.1     170  4849.1   169.8
  4859.1   169.3  4954.4  169.07  4998.4  166.69  4999.9   166.4  5031.6  168.38
  5057.4  168.65  5079.1   169.2  5149.1   169.2  5169.1   169.8  5179.1   169.6
  5309.1   170.4  5339.1   170.1  5369.1   170.3  5389.1   170.9  5440.3   170.9
  5529.1   171.1  5624.2   170.9  5654.2   170.5  5664.2   170.6  5684.2   171.4
#Mann= 5 ,-1 , 0
  4309.1    .045       0  4690.9     .09       0  4954.4     .05       0
  5057.4    .045       0  5440.3     .06       0
Bank Sta=4954.4,5057.4
XS Rating Curve= 0
Exp/Cntr=.3,.1

Type RM Length L Ch R = 1 ,3342.1  ,274.19,268.4,268.3
BEGIN DESCRIPTION:
Cross Section XS10
END DESCRIPTION:
XS GIS Cut Line= 2
     3006165.838   13936416.3516    3004759.2897   13936374.1995
#Sta/Elev= 30
  4321.8   172.3  4361.8     172  4391.8   172.1  4431.8   171.7  4461.8   172.1
  4489.2  171.92  4681.8   170.9  4691.8   170.6  4841.8   169.8  4881.8   169.4
  4890.3  168.77  4954.4  168.83  4990.4  167.17  4999.9  166.16  5012.8  167.11
  5031.6  168.14  5057.4  168.41  5116.3  168.44  5171.8   169.1  5261.8   169.1
  5291.8   169.7  5381.8   170.3  5391.8   170.1  5441.8   170.7  5461.8   170.5
  5681.8   170.5  5691.8   170.2  5711.8   170.2  5721.8   170.9  5728.9   171.1
#Mann= 5 ,-1 , 0
  4321.8     .07       0  4489.2    .045       0  4954.4    .055       0
  5057.4    .045       0  5728.9      .2       0
#XS Ineff= 2 , 0
       0                    5680       0   170.5
Permanent Ineff=
       F       F
Bank Sta=4954.4,5057.4
XS Rating Curve= 0
Exp/Cntr=.3,.1

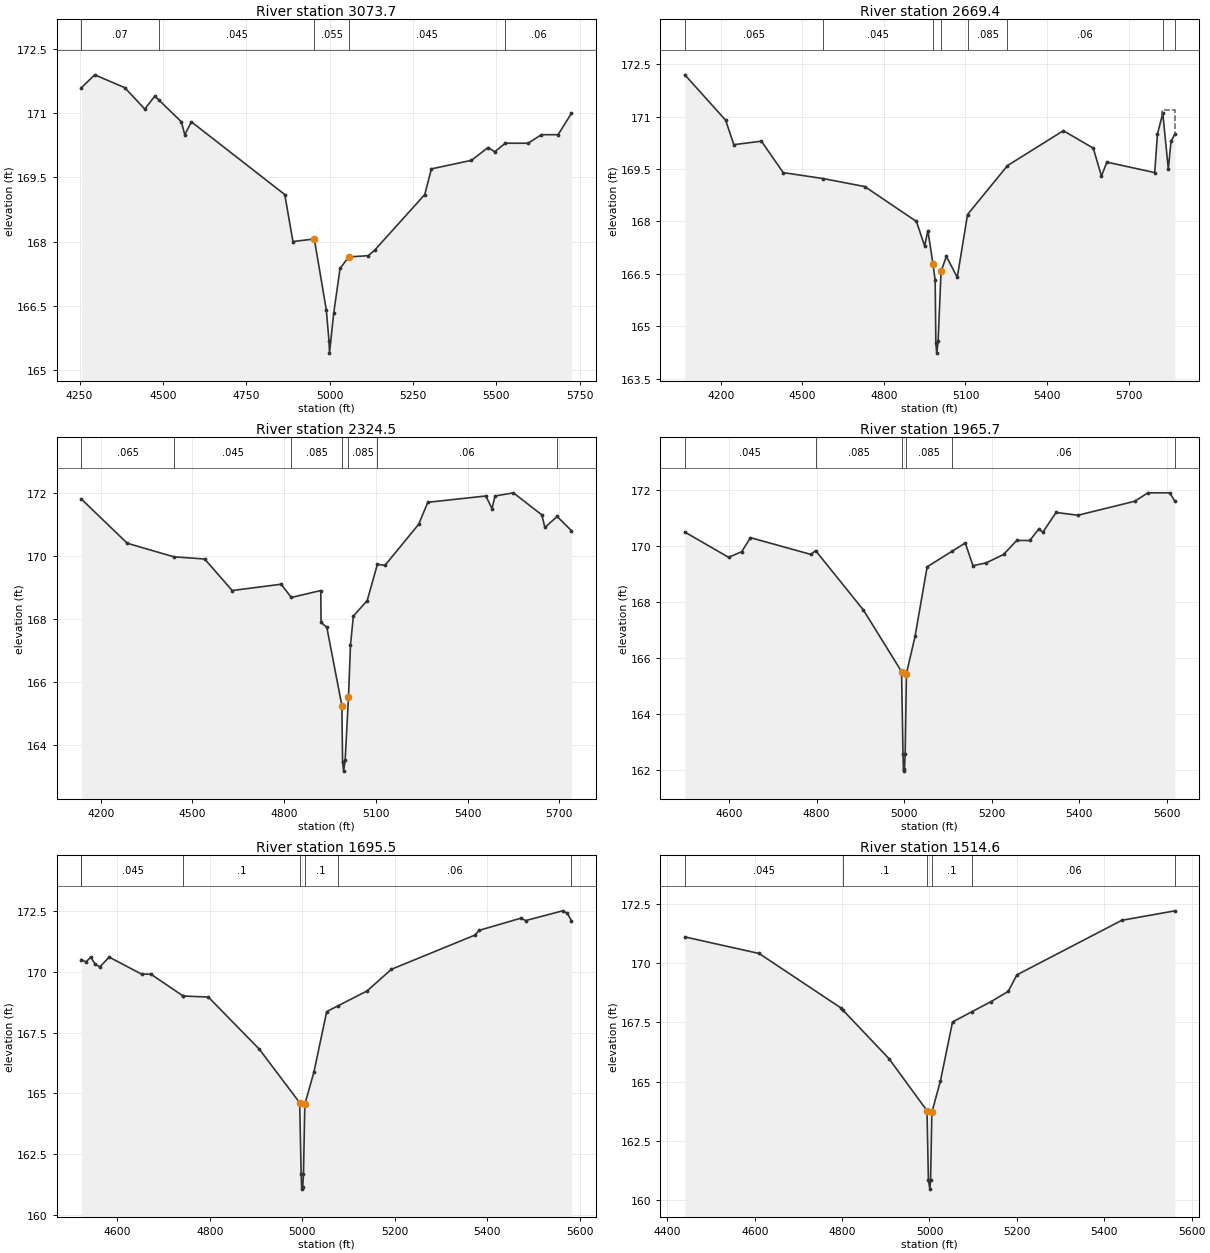
Type RM Length L Ch R = 1 ,3073.7  ,404.1,404.3,419.2
BEGIN DESCRIPTION:
Cross Section XS09
END DESCRIPTION:
XS GIS Cut Line= 2
    3006243.4811   13936132.3998     3004773.563   13936123.5582
#Sta/Elev= 30
  4255.7   171.6  4295.7   171.9  4385.7   171.6  4445.7   171.1  4475.7   171.4
  4488.3  171.31  4555.7   170.8  4565.7   170.5  4585.7   170.8  4865.7   169.1
  4890.3     168  4954.4  168.06  4990.4   166.4  4998.4  165.68  4999.9  165.39
  5012.8  166.34  5031.6  167.37  5057.4  167.64  5116.3  167.67  5135.7   167.8
  5285.7   169.1  5305.7   169.7  5425.7   169.9  5475.7   170.2  5495.7   170.1
  5527.3   170.3  5595.7   170.3  5635.7   170.5  5685.7   170.5  5725.7     171
#Mann= 5 ,-1 , 0
  4255.7     .07       0  4488.3    .045       0  4954.4    .055       0
  5057.4    .045       0  5527.3     .06       0
Bank Sta=4954.4,5057.4
XS Rating Curve= 0
Exp/Cntr=.3,.1

Type RM Length L Ch R = 1 ,2669.4  ,283.26,344.9,235.61
BEGIN DESCRIPTION:
Cross Section XS08
END DESCRIPTION:
XS GIS Cut Line= 2
    3006534.8295   13935772.1195    3004734.0997   13935719.2387
#Sta/Elev= 30
  4068.4   172.2  4218.4   170.9  4248.4   170.2  4349.9   170.3  4429.9   169.4
    4576  169.23  4729.9     169  4919.9     168  4949.9   167.3  4961.9  167.74
  4980.9  166.77  4988.7  166.31  4991.1  164.52  4994.4  164.23  4999.4  164.57
  5010.4  166.58  5029.9     167  5069.9   166.4  5107.7   168.2  5254.5   169.6
  5459.9   170.6  5569.9   170.1  5599.9   169.3  5619.9   169.7  5795.8   169.4
  5805.8   170.5  5825.5   171.1  5845.8   169.5  5855.8   170.3  5869.9   170.5
#Mann= 8 ,-1 , 0
  4068.4    .065       0    4576    .045       0  4980.9    .065       0
  5010.4    .045       0  5107.7    .085       0  5254.5     .06       0
  5825.5    .045       0  5869.9      .2       0
#XS Ineff= 2 ,-1
    5458    5810   170.5    5823  5869.9   171.2
Permanent Ineff=
       F       F
Bank Sta=4980.9,5010.4
XS Rating Curve= 0
Exp/Cntr=.3,.1

Type RM Length L Ch R = 1 ,2324.5  ,373.42,358.8,341.66
BEGIN DESCRIPTION:
Cross Section XS07
END DESCRIPTION:
XS GIS Cut Line= 2
    3006341.3171   13935483.1167    3004739.1046   13935539.2828
#Sta/Elev= 30
  4136.6   171.8  4286.6   170.4    4439  169.97  4539.9   169.9  4629.9   168.9
  4789.9   169.1  4823.4  168.68  4919.9   168.9  4920.6  167.89  4939.6  167.73
  4988.7  165.25  4991.1  163.46  4994.4  163.17  4999.4  163.51  5010.4  165.52
  5016.9  167.17  5026.4  168.09  5071.6  168.58  5104.9  169.73  5129.9   169.7
  5239.9     171  5269.9   171.7  5459.9   171.9  5479.9   171.5  5489.9   171.9
  5549.9     172    5643   171.3    5653   170.9    5693  171.25  5739.8   170.8
#Mann= 7 ,-1 , 0
  4136.6    .065       0    4439    .045       0  4823.4    .085       0
  4988.7    .065       0  5010.4    .085       0  5104.9     .06       0
    5693    .045       0
Bank Sta=4988.7,5010.4
XS Rating Curve= 0
Exp/Cntr=.3,.1

Type RM Length L Ch R = 1 ,1965.7  ,233.52,270.2,276.8
BEGIN DESCRIPTION:
Cross Section XS06
END DESCRIPTION:
XS GIS Cut Line= 2
     3005958.362   13935150.5344    3004839.2511   13935200.6832
#Sta/Elev= 30
  4498.8   170.5  4598.8   169.6  4628.8   169.8  4648.8   170.3  4787.5   169.7
  4797.6  169.84    4907  167.72  4994.3  165.52  4997.5  162.59  4998.7  161.97
  5000.9  162.06  5002.5  162.59  5005.4  165.45  5025.1  166.78  5052.7  169.26
  5109.1  169.81  5139.9  170.11  5157.5   169.3  5187.5   169.4  5227.5   169.7
  5257.5   170.2  5287.5   170.2  5307.5   170.6  5317.5   170.5  5347.5   171.2
  5397.5   171.1  5527.5   171.6  5557.5   171.9  5607.5   171.9  5619.1   171.6
#Mann= 6 ,-1 , 0
  4498.8    .045       0  4797.6    .085       0  4994.3    .065       0
  5005.4    .085       0  5109.1     .06       0  5619.1      .2       0
Bank Sta=4994.3,5005.4
XS Rating Curve= 0
Exp/Cntr=.3,.1

Type RM Length L Ch R = 1 ,1695.5  ,177.86,180.9,180.78
BEGIN DESCRIPTION:
Cross Section XS05
END DESCRIPTION:
XS GIS Cut Line= 2
    3005877.4496   13935029.8685    3004845.9062   13934790.2842
#Sta/Elev= 30
  4522.6   170.5  4532.6   170.4  4542.6   170.6  4552.6   170.3  4562.6   170.2
  4582.6   170.6  4652.6   169.9  4672.6   169.9  4742.6     169  4743.2     169
  4796.8  168.96    4907  166.82  4994.3  164.62  4997.5  161.69  4998.7  161.07
  5000.9  161.16  5002.5  161.69  5005.4  164.55  5025.1  165.88  5052.7  168.36
  5076.2  168.59  5139.9  169.21  5192.6   170.1  5372.6   171.5  5382.6   171.7
  5472.6   172.2  5482.6   172.1  5562.6   172.5  5572.6   172.4  5581.6   172.1
#Mann= 7 , 1 , 0
  4522.6      .2       0  4522.6    .045       0  4743.2      .1       0
  4994.3     .07       0  5005.4      .1       0  5076.2     .06       0
  5581.6      .2       0
Bank Sta=4994.3,5005.4
XS Rating Curve= 0
Exp/Cntr=.3,.1

Type RM Length L Ch R = 1 ,1514.6  ,61.8,62.3,62.4
BEGIN DESCRIPTION:
Cross Section XS04
END DESCRIPTION:
XS GIS Cut Line= 2
    3006019.4254   13934901.2029    3004936.8595   13934608.3777
#Sta/Elev= 18
  4440.1   171.1  4610.1   170.4  4796.8  168.11  4800.9  168.03    4907  165.97
  4994.3  163.77  4997.5  160.84  5000.9  160.46  5002.5  160.84  5005.4   163.7
  5025.1  165.03  5052.7  167.51  5097.6  167.95  5139.9  168.36  5180.1   168.8
  5200.1   169.5  5440.1   171.8  5561.6   172.2
#Mann= 6 ,-1 , 0
  4440.1    .045       0  4800.9      .1       0  4994.3     .07       0
  5005.4      .1       0  5097.6     .06       0  5561.6      .2       0
Bank Sta=4994.3,5005.4
XS Rating Curve= 0
Exp/Cntr=.5,.3