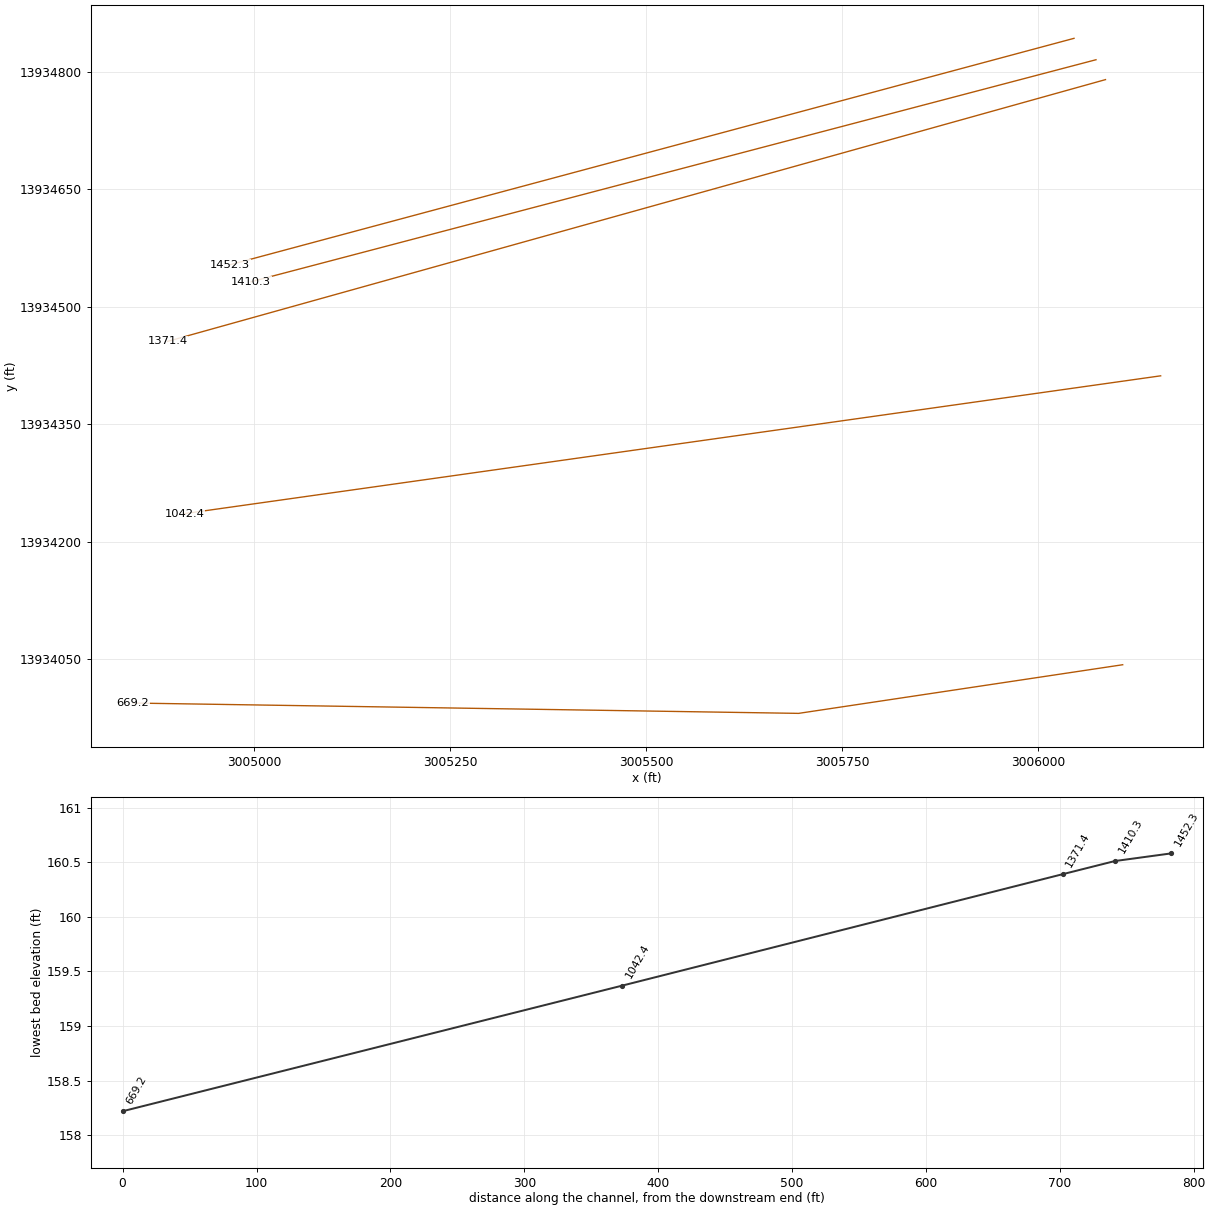
HEC-RAS study L109-00-00.prj: L1090000

--- L109-00-00.g01 (geometry) --- (continued)

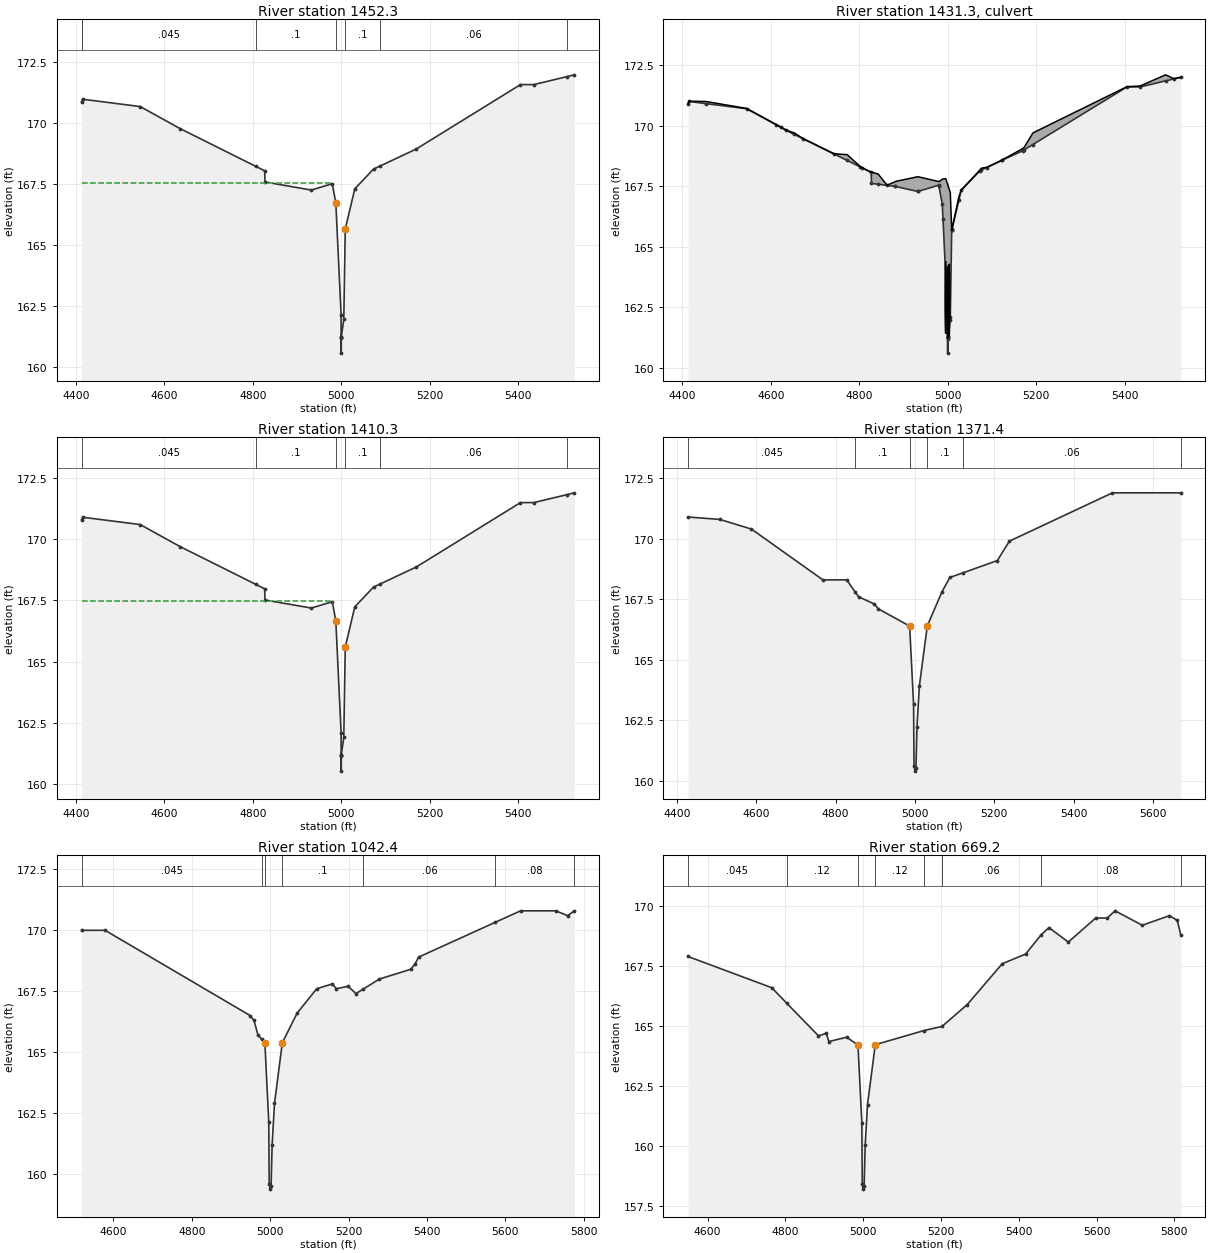
Type RM Length L Ch R = 1 ,1452.3  ,42,42,42
BEGIN DESCRIPTION:
Upstream Section of Bridge/Culvert/Weir
END DESCRIPTION:
XS GIS Cut Line= 2
    3006045.5647   13934842.8233    3004969.3612   13934553.7604
#Sta/Elev= 25
  4412.8  170.88  4415.4  170.98  4545.4  170.68  4635.4  169.78  4806.8  168.23
  4826.9  168.05  4827.7  167.59  4932.4  167.26  4979.8  167.52  4987.8  166.73
  4999.7  162.16  4999.8  161.26  4999.9  161.18    5000  160.58  5000.1  161.23
  5005.8  161.96  5009.1  165.66  5030.7  167.31  5073.1  168.12  5088.5  168.25
  5169.6  168.94  5405.4  171.58  5435.4  171.58  5511.5  171.91  5527.1  171.98
#Mann= 7 , 1 , 0
  4412.8      .2       0  4412.8    .045       0  4806.8      .1       0
  4987.8     .07       0  5009.1      .1       0  5088.5     .06       0
  5511.5      .2       0
#XS Ineff= 2 , 0
       0  4977.8  167.54  5019.1       0  165.69
Permanent Ineff=
       F       F
Bank Sta=4987.8,5009.1
XS Rating Curve= 0
Exp/Cntr=.5,.3

Type RM Length L Ch R = 2 ,1431.3  ,,,
BEGIN DESCRIPTION:
1400' US CONFLUENCE L100
Structure ID: L109-00-00-S03A
END DESCRIPTION:
Bridge Culvert--1,0,-1,-1, 0
Deck Dist Width WeirC Skew NumUp NumDn MinLoCord MaxHiCord MaxSubmerge Is_Ogee
10,22,2.6,0, 52, 52, , , .95, 0, 1,1,,
  4412.8  4415.4  4452.8  4545.4  4612.8  4622.8  4635.4  4652.8  4672.8  4742.8
  4772.8  4802.8  4806.8  4826.9  4827.7  4842.8  4862.8  4879.9  4880.9  4932.4
  4932.5  4979.8  4980.3  4987.8  4989.4  4995.6  4999.7  4999.8  4999.9    5000
  5000.1  5000.2  5005.8  5005.9  5009.1  5009.4  5009.8  5025.4  5030.7  5073.1
  5076.1  5088.5  5122.2  5122.8  5169.6  5172.8  5192.8  5405.4  5435.4  5492.8
  5511.5  5527.1
   170.9  171.01     171  170.71  170.04  169.94  169.81   169.7  169.47  168.84
   168.8   168.3  168.26  168.08  168.08     168  167.54  167.67  167.69  167.89
  167.89  167.69  167.69  167.78   167.8  167.81  167.58  167.57  167.57  167.56
  167.56  167.55  167.24  167.23  165.69  165.71  165.74  167.06  167.34  168.17
  168.24  168.28  168.57  168.58  169.05   169.1   169.7  171.61  171.64   172.1
  171.94     172
   170.9     171  170.91   170.7  170.03  169.93   169.8  169.64  169.46  168.83
  168.56  168.29  168.25  168.07  167.61  167.58  167.53  167.49  167.49  167.28
  167.28  167.54  167.49  166.75  166.14  163.75  162.18  161.28   161.2   160.6
  161.25  161.26  161.98  162.09  165.68   165.7  165.73  166.93  167.33  168.14
  168.17  168.27  168.56  168.57  168.96     169  169.22   171.6   171.6  171.85
  171.93     172
  4412.8  4415.4  4452.8  4545.4  4612.8  4622.8  4635.4  4652.8  4672.8  4742.8
  4772.8  4802.8  4806.8  4826.9  4827.7  4842.8  4862.8  4879.9  4880.9  4932.4
  4932.5  4979.8  4980.3  4987.8  4989.4  4995.6  4999.7  4999.8  4999.9    5000
  5000.1  5000.2  5005.8  5005.9  5009.1  5009.4  5009.8  5025.4  5030.7  5073.1
  5076.1  5088.5  5122.2  5122.8  5169.6  5172.8  5192.8  5405.4  5435.4  5492.8
  5511.5  5527.1
   170.9  171.01     171  170.71  170.04  169.94  169.81   169.7  169.47  168.84
   168.8   168.3  168.26  168.08  168.08     168  167.54  167.67  167.69  167.89
  167.89  167.69  167.69  167.78   167.8  167.81  167.58  167.57  167.57  167.56
  167.56  167.55  167.24  167.23  165.69  165.71  165.74  167.06  167.34  168.17
  168.24  168.28  168.57  168.58  169.05   169.1   169.7  171.61  171.64   172.1
  171.94     172
  170.84  170.94  170.85  170.64  169.97  169.87  169.74  169.58   169.4  168.77
   168.5  168.23  168.19  168.01  167.55  167.52  167.47  167.43  167.43  167.22
  167.22  167.48  167.43  166.69  166.08  163.69  162.12  161.22  161.14  160.54
  161.19   161.2  161.92  162.03  165.62  165.64  165.67  166.87  167.27  168.08
  168.11  168.21   168.5  168.51   168.9  168.94  169.16  171.54  171.54  171.79
  171.87  171.94
BR Coef= 1 , 0 , 0 ,1.25, 0 ,,,.8,-1,2,0,
WSPro=,,,, 1 ,,,, 0 ,,,, 0 ,,,,-1 ,-1 ,-1 , 0 , 0 , 0 , 0 , 0
Culvert=1,3,,22,.027,.9,1,2,3,161.4,4995.4,160.82,4995.4,Culvert #1  , 0 ,10
Culvert Bottom n=.027
Culvert=1,3,,22,.027,.9,1,1,3,161.19,4999.7,160.56,4999.7,Culvert #2  , 0 ,10
Culvert Bottom n=.027
Culvert=1,3,,22,.027,.9,1,1,3,161.29,5003.4,160.9,5003.4,Culvert #3  , 0 ,10
Culvert Bottom n=.027
BR U #Sta/Elev= 52
  4412.8   170.9  4415.4     171  4452.8  170.91  4545.4   170.7  4612.8  170.03
  4622.8  169.93  4635.4   169.8  4652.8  169.64  4672.8  169.46  4742.8  168.83
  4772.8  168.56  4802.8  168.29  4806.8  168.25  4826.9  168.07  4827.7  167.61
  4842.8  167.58  4862.8  167.53  4879.9  167.49  4880.9  167.49  4932.4  167.28
  4932.5  167.28  4979.8  167.54  4980.3  167.49  4987.8  166.75  4989.4  166.14
  4995.6  163.75  4999.7  162.18  4999.8  161.28  4999.9   161.2    5000   160.6
  5000.1  161.25  5000.2  161.26  5005.8  161.98  5005.9  162.09  5009.1  165.68
  5009.4   165.7  5009.8  165.73  5025.4  166.93  5030.7  167.33  5073.1  168.14
  5076.1  168.17  5088.5  168.27  5122.2  168.56  5122.8  168.57  5169.6  168.96
  5172.8     169  5192.8  169.22  5405.4   171.6  5435.4   171.6  5492.8  171.85
  5511.5  171.93  5527.1     172
BR U #Mann= 6
  4412.8    .045  4806.8      .1  4987.8     .07  5009.1      .1  5088.5     .06
  5511.5      .2
BR U Banks=4987.8,5009.1
BR D #Sta/Elev= 52
  4412.8  170.84  4415.4  170.94  4452.8  170.85  4545.4  170.64  4612.8  169.97
  4622.8  169.87  4635.4  169.74  4652.8  169.58  4672.8   169.4  4742.8  168.77
  4772.8   168.5  4802.8  168.23  4806.8  168.19  4826.9  168.01  4827.7  167.55
  4842.8  167.52  4862.8  167.47  4879.9  167.43  4880.9  167.43  4932.4  167.22
  4932.5  167.22  4979.8  167.48  4980.3  167.43  4987.8  166.69  4989.4  166.08
  4995.6  163.69  4999.7  162.12  4999.8  161.22  4999.9  161.14    5000  160.54
  5000.1  161.19  5000.2   161.2  5005.8  161.92  5005.9  162.03  5009.1  165.62
  5009.4  165.64  5009.8  165.67  5025.4  166.87  5030.7  167.27  5073.1  168.08
  5076.1  168.11  5088.5  168.21  5122.2   168.5  5122.8  168.51  5169.6   168.9
  5172.8  168.94  5192.8  169.16  5405.4  171.54  5435.4  171.54  5492.8  171.79
  5511.5  171.87  5527.1  171.94
BR D #Mann= 6
  4412.8    .045  4806.8      .1  4987.8     .07  5009.1      .1  5088.5     .06
  5511.5      .2
BR D Banks=4987.8,5009.1
BC Design=,, 0 ,, 0 ,,,,,,
BC HTab HWMax=171.98

Type RM Length L Ch R = 1 ,1410.3  ,38.9,38.9,38.9
BEGIN DESCRIPTION:
Downstream Section of Bridge/Culvert/Weir
END DESCRIPTION:
XS GIS Cut Line= 2
    3006073.6112   13934815.5013    3004996.0206   13934532.0432
#Sta/Elev= 25
  4412.8  170.81  4415.4  170.91  4545.4  170.61  4635.4  169.71  4806.8  168.16
  4826.9  167.98  4827.7  167.52  4932.4  167.19  4979.8  167.45  4987.8  166.66
  4999.7  162.09  4999.8  161.19  4999.9  161.11    5000  160.51  5000.1  161.16
  5005.8  161.89  5009.1  165.59  5030.7  167.24  5073.1  168.05  5088.5  168.18
  5169.6  168.87  5405.4  171.51  5435.4  171.51  5511.5  171.84  5527.1  171.91
#Mann= 6 ,-1 , 0
  4412.8    .045       0  4806.8      .1       0  4987.8     .07       0
  5009.1      .1       0  5088.5     .06       0  5511.5      .2       0
#XS Ineff= 2 , 0
       0 4981.13  167.49 5015.77       0  165.69
Permanent Ineff=
       F       F
Bank Sta=4987.8,5009.1
XS Rating Curve= 0
Exp/Cntr=.5,.3

Type RM Length L Ch R = 1 ,1371.4  ,336.78,329,322.44
BEGIN DESCRIPTION:
Cross Section XS03
END DESCRIPTION:
XS GIS Cut Line= 2
    3006085.7089   13934790.1121    3004889.3174   13934455.8263
#Sta/Elev= 24
  4427.9   170.9  4507.9   170.8  4587.9   170.4  4767.9   168.3  4827.9   168.3
  4849.6  167.79  4857.9   167.6  4897.9   167.3  4907.9   167.1  4986.6  166.39
  4996.5  163.15  4997.6  160.61  5000.4  160.39  5002.4   160.5  5005.1  162.21
  5011.1  163.91  5031.1   166.4  5067.9   167.8  5087.9   168.4    5121  168.59
  5207.9   169.1  5237.9   169.9  5497.9   171.9  5670.1   171.9
#Mann= 6 ,-1 , 0
  4427.9    .045       0  4849.6      .1       0  4986.6     .07       0
  5031.1      .1       0    5121     .06       0  5670.1      .2       0
Bank Sta=4986.6,5031.1
XS Rating Curve= 0
Exp/Cntr=.3,.1

Type RM Length L Ch R = 1 ,1042.4  ,368.45,373.2,359.83
BEGIN DESCRIPTION:
Cross Section XS02
END DESCRIPTION:
XS GIS Cut Line= 2
    3006156.0849   13934411.8413    3004911.3099   13934235.9014
#Sta/Elev= 30
  4518.9     170  4578.9     170  4948.9   166.5  4958.9   166.3  4968.9   165.7
  4978.8  165.52  4986.6  165.37  4996.5  162.13  4997.6  159.59  5000.4  159.37
  5002.4  159.48  5005.1  161.19  5011.1  162.89  5031.1  165.38  5068.9   166.6
  5118.9   167.6  5158.9   167.8  5168.9   167.6  5198.9   167.7  5218.9   167.4
    5238  167.59  5278.9     168  5358.9   168.4  5368.9   168.6  5378.9   168.9
  5574.5  170.33  5638.9   170.8  5728.9   170.8  5758.9   170.6    5776   170.8
#Mann= 7 ,-1 , 0
  4518.9    .045       0  4978.8      .1       0  4986.6     .07       0
  5031.1      .1       0    5238     .06       0  5574.5     .08       0
    5776      .2       0
Bank Sta=4986.6,5031.1
XS Rating Curve= 0
Exp/Cntr=.3,.1

Type RM Length L Ch R = 1 ,669.2   ,0,0,0
BEGIN DESCRIPTION:
Cross Section XS01
END DESCRIPTION:
XS GIS Cut Line= 3
      3006107.64      13934042.9    3005694.2426   13933980.7885
    3004845.3325    13933993.984
#Sta/Elev= 30
  4549.6   167.9    4765   166.6  4803.1  165.96    4885   164.6    4905   164.7
  4911.7  164.36  4957.3  164.54  4986.6  164.22  4996.5  160.98  4997.6  158.44
  5000.4  158.22  5002.4  158.33  5005.1  160.04  5011.1  161.74  5031.1  164.23
  5156.6  164.82  5202.6  164.99  5267.6   165.9  5357.6   167.6  5417.6     168
    5458  168.81  5477.6   169.1  5527.6   168.5  5597.6   169.5  5627.6   169.5
  5647.6   169.8  5717.6   169.2  5787.6   169.6  5807.6   169.4  5816.6   168.8
#Mann= 8 ,-1 , 0
  4549.6    .045       0  4803.1     .12       0  4986.6     .07       0
  5031.1     .12       0  5156.6     .12       0  5202.6     .06       0
    5458     .08       0  5816.6      .2       0
Bank Sta=4986.6,5031.1
XS Rating Curve= 0
Exp/Cntr=.3,.1

Chan Stop Cuts=-1